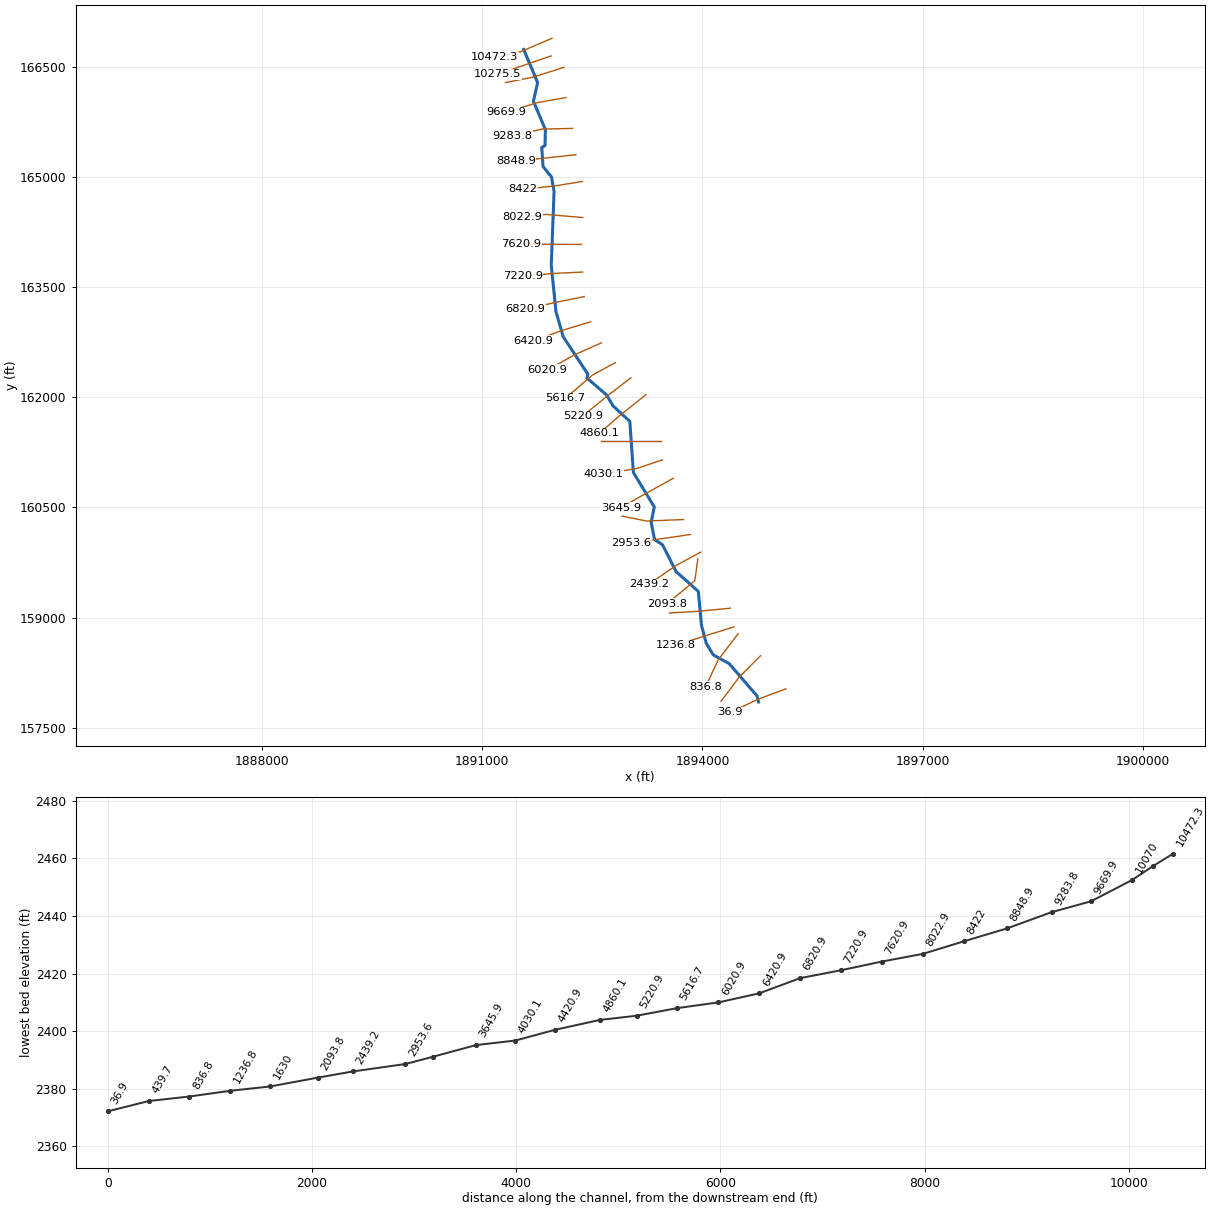
--- BigBrnch.prj (project) ---

Proj Title=BigBrnch
Current Plan=p01
Default Exp/Contr=0,0
English Units
Geom File=g01
Flow File=f01
Plan File=p01
BEGIN DESCRIPTION:
END DESCRIPTION:
DSS Export Rating Curves= 0
DSS Export Rating Curve Sorted= 0
DSS Export Volume Flow Curves= 0
DXF OffsetX= 0
DXF OffsetY= 0
DXF ScaleX= 0
DXF ScaleY= 0

--- BigBrnch.p01 (plan) ---

Plan Title=Floodplain
Program Version=4.00
Geom File=g01
Flow File=f01
K Sum by GR=0
Std Step Tol=0.01
Critical Tol=0.01
Num of Std Step Trials=20
Max Error Tol=0.3
Flow Tol Ratio=0.001
Split Flow NTrial=30
Split Flow Tol=0.02
Split Flow Ratio=0.02
Log Output Level=0
Friction Slope Method=1
Unsteady Friction Slope Method=2
Unsteady Bridges Friction Slope Method=1
Global Log Level=0
CheckData=False
Run HTab=0
Run UNet=0
Run PostProcess=0
UNET Theta=0
UNET Theta Warmup=0
UNET ZTol=0
UNET ZSATol=0
UNET MxIter=0
UNET MaxInSteps=0
UNET DtIC=0
UNET DtMin=0
UNET MaxCRTS=0
UNET WFStab=0
UNET SFStab=0
UNET WFX=0
UNET SFX=0
UNET DSS MLevel=0
UNET DZMax Abort=0
UNET Convert EG Bridges=0
UNET Use Existing IB Tables=0
UNET Froude Limit=0
UNET Froude Power=0
Write IC File=0
Echo Input=False
Echo Output=False
Write Detailed=0

--- BigBrnch.f01 (steady flow) ---

Flow Title=NFF Regression Equation
Program Version=4.00
Number of Profiles=1
Profile Names=P100yr
River Rch & RM=BigBrnch,Main      ,10472.3
125.2967
River Rch & RM=BigBrnch,Main      ,10275.5
128.2363
River Rch & RM=BigBrnch,Main      ,9669.9
167.8469
River Rch & RM=BigBrnch,Main      ,8848.9
178.7216
River Rch & RM=BigBrnch,Main      ,8422
265.6879
River Rch & RM=BigBrnch,Main      ,8422
207.8263
River Rch & RM=BigBrnch,Main      ,6820.9
294.6216
River Rch & RM=BigBrnch,Main      ,6420.9
348.2125
River Rch & RM=BigBrnch,Main      ,6020.9
350.4940
River Rch & RM=BigBrnch,Main      ,5616.7
406.4113
River Rch & RM=BigBrnch,Main      ,4860.1
410.7991
River Rch & RM=BigBrnch,Main      ,4420.9
462.5896
River Rch & RM=BigBrnch,Main      ,3222.4
504.6588
River Rch & RM=BigBrnch,Main      ,2439.2
531.5361
River Rch & RM=BigBrnch,Main      ,36.9
572.2386
Boundary for River Rch & Prof#=BigBrnch,Main      ,1
Up Type=0
Dn Type=3
Dn Slope=0.005839

--- BigBrnch.g01 (geometry) ---

Geom Title=USGS 3m DEM
Program Version=4.10

River Reach=BigBrnch        ,Main
Reach XY= 30
     1891566.168      166738.832     1891755.735      166287.906
     1891698.112       166033.97     1891861.306      165647.112
      1891855.87      165430.206     1891811.477      165404.441
     1891829.381       165144.62     1891943.828      165002.379
     1891979.363      164804.804     1891941.168      163799.595
     1892005.404      163167.651     1892102.626      162827.373
     1892439.432       162315.22     1892427.279      162263.137
     1892692.904      162033.971     1892783.182      161882.929
     1893010.612      161672.859     1893059.224      160976.679
     1893343.946      160506.193     1893300.543      160296.123
     1893347.418      160063.484     1893455.057      159992.304
     1893640.821      159625.984     1893942.904      159356.887
     1893986.307      158891.609     1894050.543       158650.29
     1894147.765      158490.568     1894363.043      158372.512
     1894740.578      157934.791     1894762.847      157850.653

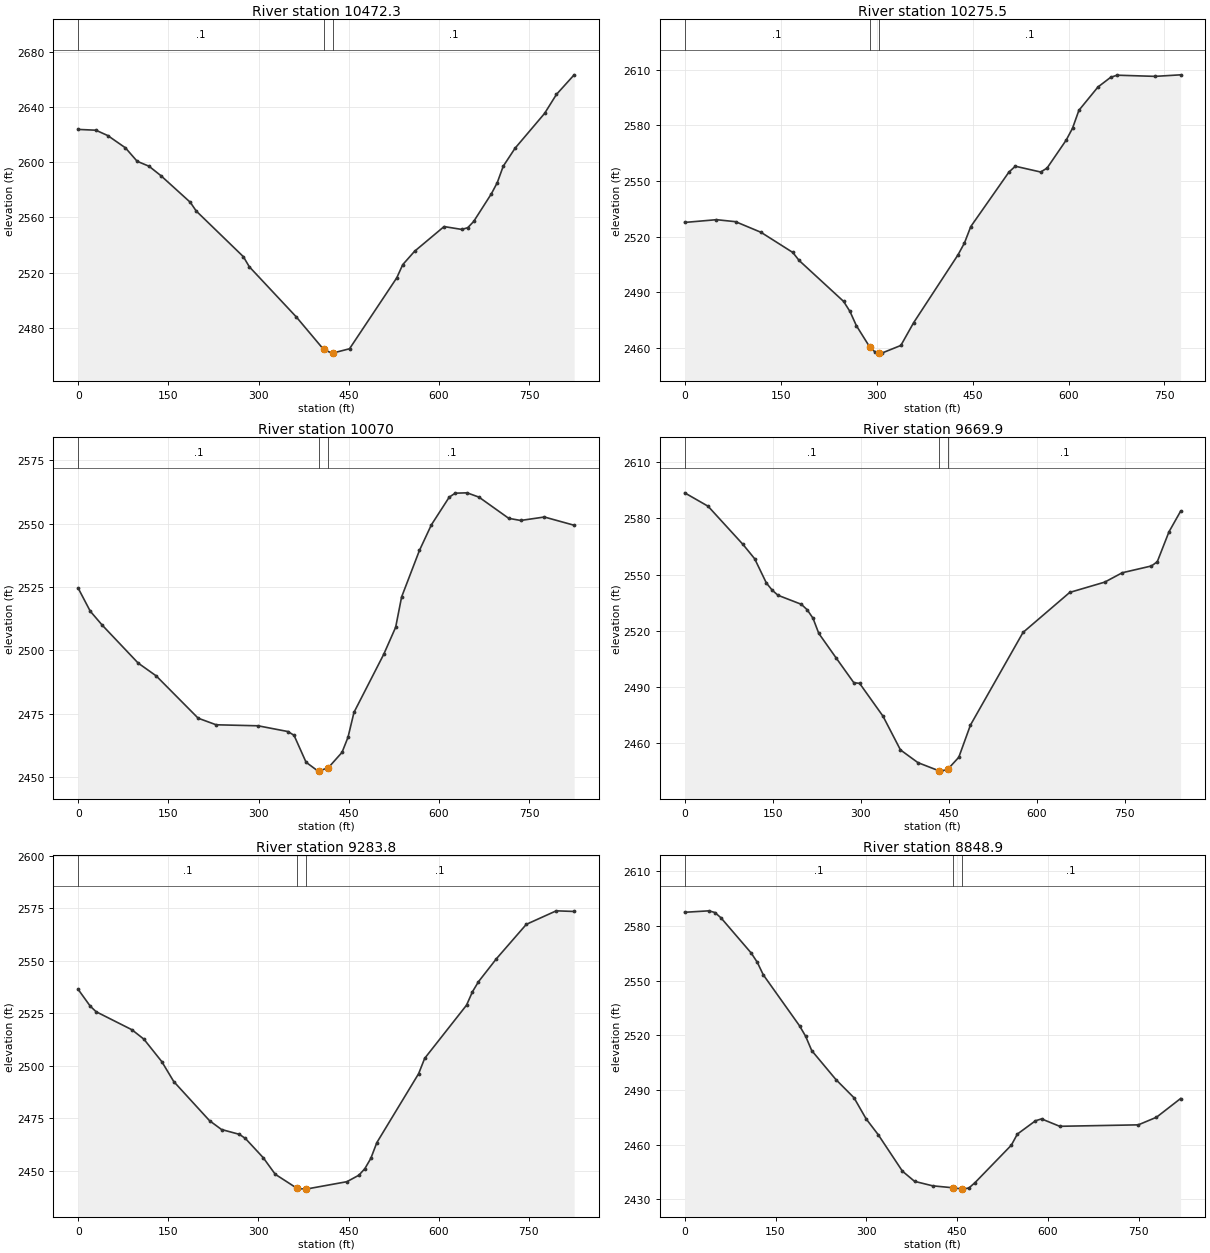
Type RM Length L Ch R = 1 ,10472.3 ,198.6,196.8,195
XS GIS Cut Line= 3
     1891951.351      166890.831     1891518.222       166705.67
      1891172.35      166630.067
#Sta/Elev= 30
       0 2623.88    29.4 2623.29    49.1 2619.43    78.5 2610.53    98.1 2600.74
   117.8 2597.16   137.4 2590.38   186.5 2570.98   196.3 2564.68   274.8 2531.52
   284.6 2524.25   363.1 2487.69   408.3 2464.21     422 2461.55   423.3 2461.57
   451.4 2464.72     530  2516.2   539.9 2525.74   559.6 2535.45   608.7 2553.38
   638.2  2551.3   648.1 2552.57   657.9 2557.06   687.4 2577.18   697.2 2585.27
   707.1 2597.16   726.7 2610.17   775.9 2635.48   795.6 2649.24   825.1 2663.48
#Mann= 3 , 0 , 0
       0      .1       0   408.3    .045       0   423.3      .1       0
Bank Sta=408.3,423.3
XS Rating Curve= 0 ,0
Exp/Cntr=0.3,0.1

Type RM Length L Ch R = 1 ,10275.5 ,204.6,204.7,203.8
XS GIS Cut Line= 2
     1891940.424      166651.038     1891207.093      166399.804
#Sta/Elev= 30
       0 2527.66    49.7 2529.14    79.5 2528.07   119.3 2522.34     169 2511.48
   178.9 2507.16   248.4 2485.11   258.4 2479.67   268.3 2472.08   289.1 2460.62
   298.1 2457.67   304.1 2457.41   308.1 2457.23   337.9 2461.37   357.8 2473.59
   427.3 2510.23   437.3 2516.58   447.2 2525.43   506.8 2554.78   516.8 2557.95
   556.5 2554.83   566.5 2556.98   596.3 2572.01   606.2 2578.39   616.2 2588.08
     646 2600.65   665.8 2605.85   675.8 2607.01   735.4 2606.38   775.2 2607.21
#Mann= 3 , 0 , 0
       0      .1       0   289.1    .045       0   304.1      .1       0
Bank Sta=289.1,304.1
XS Rating Curve= 0 ,0
Exp/Cntr=0.3,0.1

Type RM Length L Ch R = 1 ,10070   ,400.7,399.8,399
XS GIS Cut Line= 3
      1892115.28      166494.944     1891687.183      166360.155
     1891317.957      166288.456
#Sta/Elev= 30
       0 2524.55      20  2515.5    39.9    2510    99.7 2495.03   129.7 2489.98
   199.5 2473.29   229.4 2470.69   299.2 2470.29   349.1 2468.01     359 2466.53
     379 2455.91     399 2452.41   401.1  2452.5   416.1 2453.78   438.8 2459.81
   448.8 2465.81   458.7  2475.6   508.2  2498.5     528 2509.16   537.9  2521.1
   567.6 2539.48   587.4 2549.55   617.1 2560.47     627 2562.04   646.8 2562.18
   666.6 2560.48   716.1 2552.12   735.9 2551.28   775.4 2552.64   824.9 2549.39
#Mann= 3 , 0 , 0
       0      .1       0   401.1    .045       0   416.1      .1       0
Bank Sta=401.1,416.1
XS Rating Curve= 0 ,0
Exp/Cntr=0.3,0.1

Type RM Length L Ch R = 1 ,9669.9  ,391.6,386.1,380.5
XS GIS Cut Line= 3
     1892143.467      166083.818     1891751.941      166014.679
     1891324.568      165881.124
#Sta/Elev= 30
       0 2593.65    39.8 2586.51    99.4 2566.09   119.3 2558.45   139.2 2545.53
   149.1 2541.71     159 2538.96   198.8 2534.14   208.7 2531.25   218.7 2526.71
   228.6 2518.59   258.4 2505.39   288.2 2492.32   298.2 2491.91     338 2474.42
   367.8 2456.39   397.6  2449.6   433.8  2445.2   437.4 2445.07   448.8  2446.2
   467.2 2452.46   487.1 2469.68   576.7 2519.12   656.3 2540.48     716 2545.98
   745.8 2550.98   795.6 2554.61   805.5 2556.85   825.4  2572.8   845.3 2583.85
#Mann= 3 , 0 , 0
       0      .1       0   433.8    .045       0   448.8      .1       0
Bank Sta=433.8,448.8
XS Rating Curve= 0 ,0
Exp/Cntr=0.3,0.1

Type RM Length L Ch R = 1 ,9283.8  ,446.8,435,437.3
XS GIS Cut Line= 3
     1892231.747      165663.388     1891814.525      165653.937
     1891416.858      165562.168
#Sta/Elev= 30
       0 2536.35    19.9 2528.44    29.8 2525.74    89.4 2517.16   109.3 2512.69
   139.1 2501.99     159 2492.51   218.6 2473.87   238.5 2469.68   268.3 2467.37
   278.2 2465.43     308 2456.24   327.9 2448.38   364.4 2441.64   377.6  2441.3
   379.4 2441.32   447.2 2444.84   467.1 2447.92     477 2451.02     487 2455.94
     497 2463.44   566.6 2496.28   576.6 2503.54   646.3 2528.87   656.2 2535.28
   666.2 2540.04     696 2550.96   745.8 2567.34   795.6 2573.77   825.4 2573.47
#Mann= 3 , 0 , 0
       0      .1       0   364.4    .045       0   379.4      .1       0
Bank Sta=364.4,379.4
XS Rating Curve= 0 ,0
Exp/Cntr=0.3,0.1

Type RM Length L Ch R = 1 ,8848.9  ,425.3,426.7,426.8
XS GIS Cut Line= 3
     1892275.396      165304.482     1891868.279      165260.127
     1891460.759      165219.949
#Sta/Elev= 30
       0 2587.38      40 2588.18    49.9 2587.26    59.9 2584.36   109.9 2565.04
   119.9 2559.99   129.8 2553.12   189.8 2525.12   199.8 2519.41   209.8  2511.6
   249.7 2495.74   279.7 2485.73   299.6  2474.2   319.6 2465.52   359.6 2445.52
   379.6 2439.95   409.5 2437.49   442.4 2436.44   457.4 2435.77   459.5 2435.68
   469.4 2436.32   479.4 2439.22   539.4 2459.75   549.4 2465.84   579.3 2473.13
   589.3 2474.17   619.3 2470.11   749.1  2470.9   779.1 2475.06     819 2485.33
#Mann= 3 , 0 , 0
       0      .1       0   442.4    .045       0   457.4      .1       0
Bank Sta=442.4,457.4
XS Rating Curve= 0 ,0
Exp/Cntr=0.3,0.1

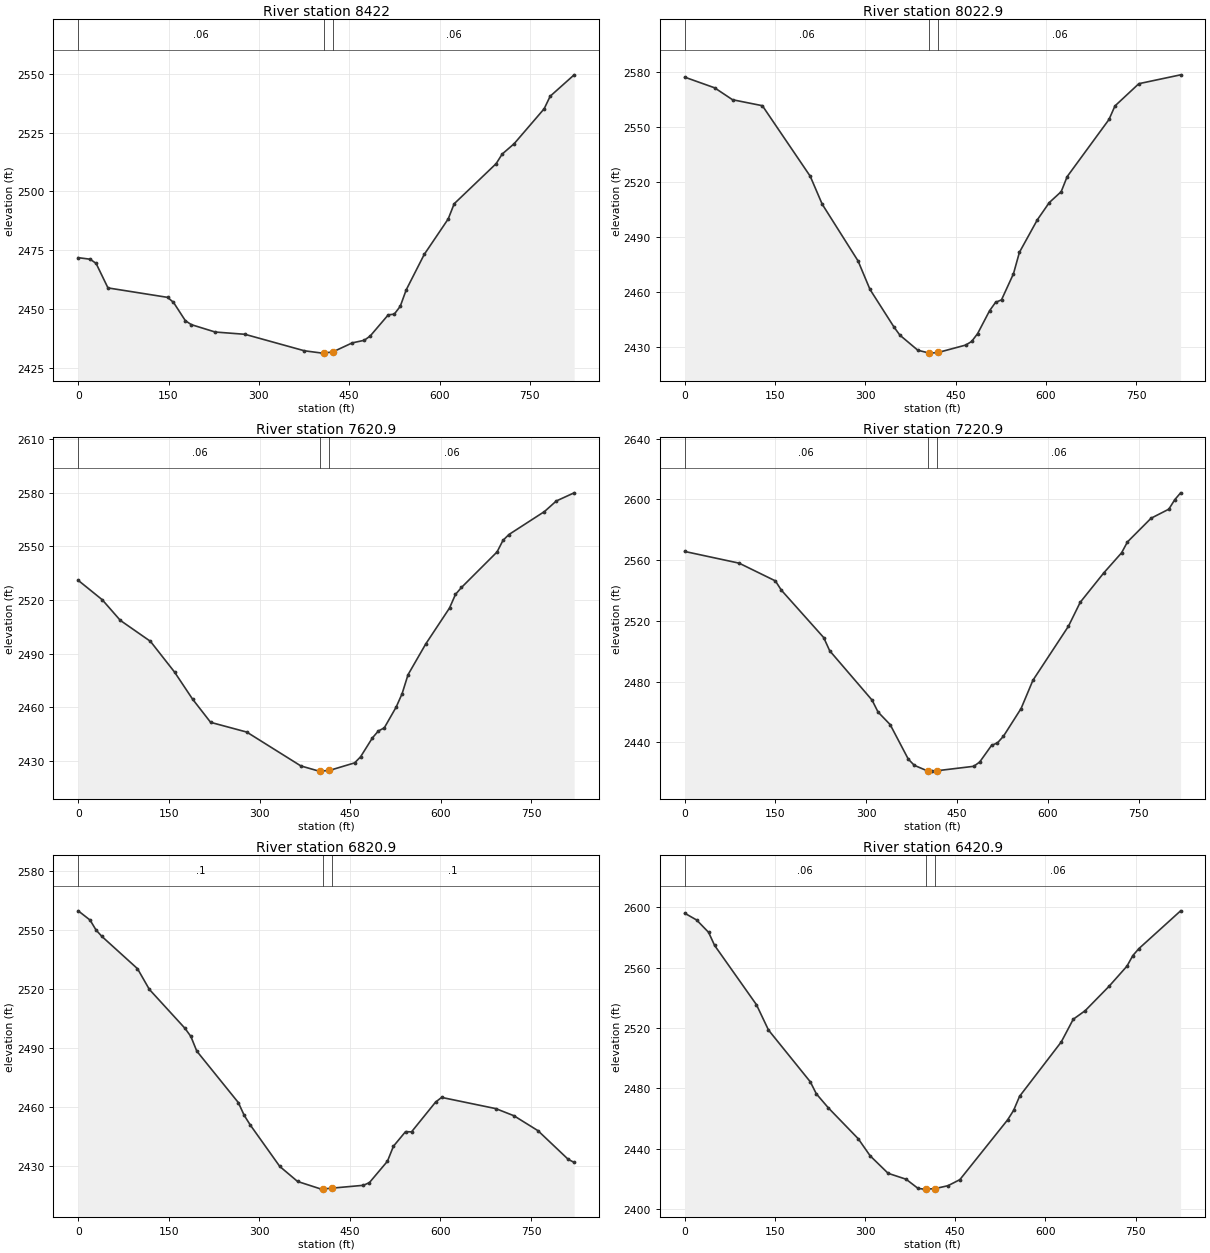
Type RM Length L Ch R = 1 ,8422    ,404.4,398.9,394.8
XS GIS Cut Line= 3
     1892366.851      164940.332     1891956.793      164875.182
     1891550.448      164835.161
#Sta/Elev= 30
       0  2471.8    19.8 2471.14    29.7 2469.36    49.4 2458.92   148.3  2454.9
   158.2 2452.78   177.9 2444.97   187.8 2443.28   227.4 2440.14   276.8 2439.17
   375.7 2432.14   405.3 2431.15   407.7 2431.18   422.7 2431.66     455 2435.51
     475 2436.62   484.9 2438.46   514.8 2447.45   524.8 2447.75   534.7 2451.07
   544.7 2458.13   574.5 2473.15   614.4  2488.3   624.3 2494.76     694 2511.85
     704 2515.92   723.9 2520.34   773.7 2535.21   783.7 2540.55   823.5 2549.66
#Mann= 3 , 0 , 0
       0     .06       0   407.7    .045       0   422.7     .06       0
Bank Sta=407.7,422.7
XS Rating Curve= 0 ,0
Exp/Cntr=0.3,0.1

Type RM Length L Ch R = 1 ,8022.9  ,400.2,401.9,403.7
XS GIS Cut Line= 3
     1892371.357      164449.583     1891866.483      164491.456
     1891551.428      164453.254
#Sta/Elev= 30
       0 2577.24    49.7 2571.43    79.5 2564.93   129.1 2561.67   208.6 2523.23
   228.5 2507.99   288.1 2477.05   307.9 2461.54   347.7 2441.07   357.6 2436.61
   387.4 2428.39   406.1 2426.87   407.3 2426.82   421.1 2427.17   466.9 2431.21
   476.8 2433.19   486.7 2437.45   506.6 2449.94   516.5 2454.48   526.4 2455.86
   546.3  2470.1   556.2 2481.79     586 2499.52   605.8 2508.88   625.6 2514.84
   635.5 2523.02     705 2554.17   714.9 2561.54   754.6 2573.67     824  2578.5
#Mann= 3 , 0 , 0
       0     .06       0   406.1    .045       0   421.1     .06       0
Bank Sta=406.1,421.1
XS Rating Curve= 0 ,0
Exp/Cntr=0.3,0.1

Type RM Length L Ch R = 1 ,7620.9  ,398.8,399.9,402.1
XS GIS Cut Line= 3
     1892352.676      164083.157     1891944.336      164085.054
     1891531.975      164085.146
#Sta/Elev= 30
       0 2530.98    39.8  2520.1    69.7 2508.55   119.5 2496.83   159.4 2479.62
   189.2 2464.49   219.1 2451.47   278.9 2446.02   368.5 2427.05   398.4 2424.15
   400.8 2424.16   415.8 2424.55   457.4 2428.77   467.2 2432.14   486.9 2442.78
   496.7 2446.63   506.5 2448.37   526.2 2460.04     536 2467.53   545.8 2478.14
   575.2 2495.41   614.5  2515.5   624.3  2523.1   634.2 2526.97   693.1 2546.87
   702.9 2553.34   712.7 2556.62   771.6  2569.5   791.2 2575.42   820.7 2579.98
#Mann= 3 , 0 , 0
       0     .06       0   400.8    .045       0   415.8     .06       0
Bank Sta=400.8,415.8
XS Rating Curve= 0 ,0
Exp/Cntr=0.3,0.1

Type RM Length L Ch R = 1 ,7220.9  ,396.6,400,403
XS GIS Cut Line= 3
     1892367.788      163706.538     1891958.845      163687.063
     1891550.614      163648.691
#Sta/Elev= 30
       0 2565.73    89.9 2558.03   149.8 2546.36   159.8 2540.22   229.7 2509.04
   239.6 2500.36   309.6 2467.88   319.5 2460.02   339.5 2451.76   369.5    2429
   379.4 2424.95   401.9 2421.14   409.4 2421.13   416.9 2421.39   477.7 2424.31
   487.5 2427.17     507 2438.06   516.8 2439.73   526.6 2444.06   555.8 2462.33
   575.4 2480.95     634 2516.46   653.5 2532.25   692.5 2551.64   721.8  2564.8
   731.6 2572.02   770.6  2587.6   799.9 2593.56   809.7 2599.78   819.4 2604.32
#Mann= 3 , 0 , 0
       0     .06       0   401.9    .045       0   416.9     .06       0
Bank Sta=401.9,416.9
XS Rating Curve= 0 ,0
Exp/Cntr=0.3,0.1

Type RM Length L Ch R = 1 ,6820.9  ,397.7,400,402.8
XS GIS Cut Line= 3
     1892390.099      163372.484     1891985.848      163290.556
     1891587.507      163197.676
#Sta/Elev= 30
       0  2559.8    19.6 2555.11    29.5 2550.07    39.3 2546.77    98.2  2530.4
   117.8  2519.9   176.8 2500.12   186.6 2495.98   196.4 2488.53   265.2 2462.39
     275 2455.86   284.8 2451.08   333.9 2429.92   363.4 2422.29   402.6  2418.4
     405 2418.45     420 2418.89   472.3 2420.34   482.3 2421.69   512.2 2432.56
   522.2 2440.22   542.2  2447.6   552.1 2447.49     592 2462.63     602    2465
   691.8  2459.3   721.7 2455.69   761.6 2448.09   811.5 2433.58   821.5 2431.96
#Mann= 3 , 0 , 0
       0      .1       0     405    .045       0     420      .1       0
Bank Sta=405,420
XS Rating Curve= 0 ,0
Exp/Cntr=0.3,0.1

Type RM Length L Ch R = 1 ,6420.9  ,397.3,399.9,398.7
XS GIS Cut Line= 3
     1892478.238      163029.671     1892087.689        162911.2
     1891696.003      162768.675
#Sta/Elev= 30
       0 2596.12    19.9 2591.59    39.8 2583.41    49.8 2574.72   119.4 2535.42
   139.4 2518.63     209 2484.27     219 2476.32   238.9 2467.05   288.7 2446.54
   308.6 2435.17   338.4 2423.62   368.3 2419.69   388.2  2413.6   398.2 2413.13
   400.6 2413.15   415.6 2413.41   437.9 2415.39   457.7 2419.42   537.1 2459.04
   547.1 2465.33     557 2474.66   626.4 2510.76   646.3 2525.78   666.2 2531.48
   705.8 2547.61   735.6 2560.97   745.5 2568.05   755.5 2572.63   824.9 2597.68
#Mann= 3 , 0 , 0
       0     .06       0   400.6    .045       0   415.6     .06       0
Bank Sta=400.6,415.6
XS Rating Curve= 0 ,0
Exp/Cntr=0.3,0.1

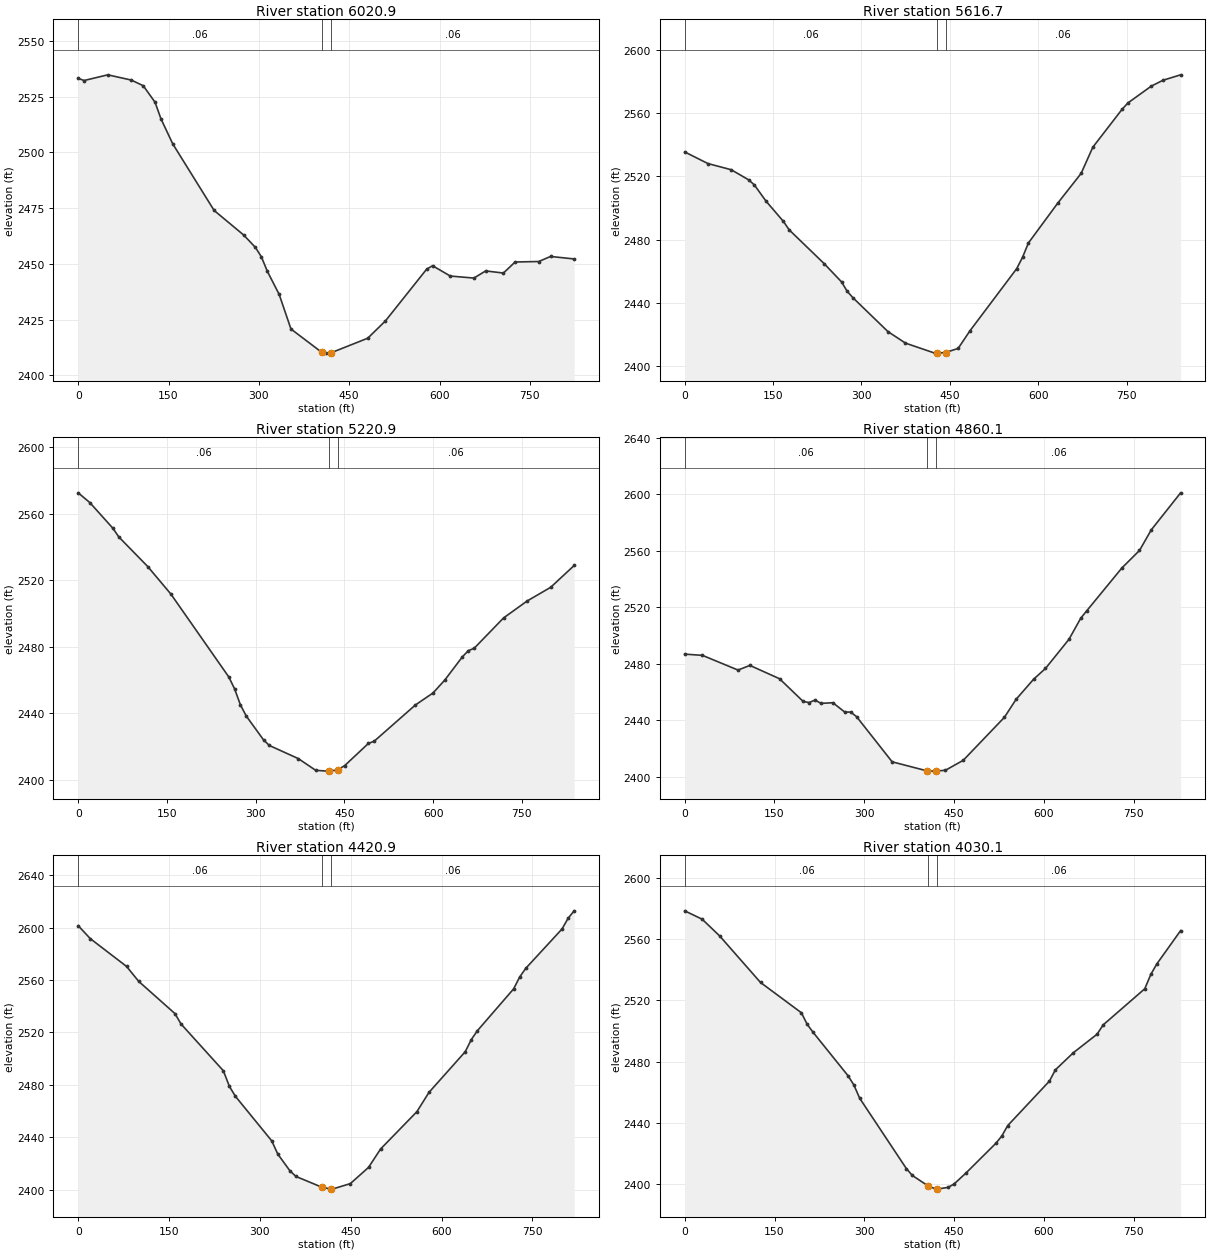
Type RM Length L Ch R = 1 ,6020.9  ,397.1,404.1,407.4
XS GIS Cut Line= 3
     1892623.822      162742.312     1892247.452        162574.2
     1891889.009      162372.303
#Sta/Elev= 30
       0 2533.16     9.8  2532.2    49.1 2534.75    88.3 2532.39     108 2529.86
   127.6 2522.46   137.4 2515.04     157 2503.79   225.7 2473.95   274.8 2462.93
   294.4 2457.34   304.2 2453.14   314.1 2446.65   333.7 2436.33   353.3  2420.8
   404.7 2410.29   412.2 2409.98   419.7 2410.11   480.8 2416.67   510.2 2424.42
   578.7 2447.64   588.5 2449.16   617.9 2444.54   657.1 2443.63   676.7 2446.84
   706.1 2445.88   725.6 2450.84   764.8 2451.05   784.4 2453.32   823.6  2452.2
#Mann= 3 , 0 , 0
       0     .06       0   404.7    .045       0   419.7     .06       0
Bank Sta=404.7,419.7
XS Rating Curve= 0 ,0
Exp/Cntr=0.3,0.1

Type RM Length L Ch R = 1 ,5616.7  ,391.1,395.8,427.8
XS GIS Cut Line= 3
      1892813.54       162472.44     1892501.527      162303.312
     1892132.181      161985.991
#Sta/Elev= 30
       0 2535.57    39.4 2528.19    78.9 2524.28   108.4  2517.9   118.3 2514.63
     138 2504.39   167.6  2491.5   177.4 2486.14   236.6 2464.79   266.2 2453.18
     276  2447.1   285.9    2443     345 2421.65   374.8 2414.33   424.5 2407.99
     428 2408.01     443 2408.38   464.2 2410.99   484.1 2422.08   563.6 2461.57
   573.5 2468.76   583.5 2477.86   633.2 2503.07   672.9 2521.92   692.8 2538.57
   742.5 2562.61   752.4 2566.63   792.2 2577.32     812 2581.01   841.8 2584.44
#Mann= 3 , 0 , 0
       0     .06       0     428    .045       0     443     .06       0
Bank Sta=428,443
XS Rating Curve= 0 ,0
Exp/Cntr=0.3,0.1

Type RM Length L Ch R = 1 ,5220.9  ,372.3,360.7,358.6
XS GIS Cut Line= 3
      1893024.91      162266.786     1892684.224      162003.168
     1892369.193       161744.63
#Sta/Elev= 30
       0  2572.6    19.6 2566.75    58.7 2551.28    68.5 2546.14   117.5 2528.31
   156.6 2511.78   254.5 2461.97   264.3 2454.83   274.1 2445.25   283.9 2438.55
   313.3 2424.11   323.1 2420.77     372  2412.9   401.4 2405.85     421 2405.36
   423.3 2405.36   438.3 2406.05   450.6 2408.73   490.4 2421.97   500.4 2423.37
   569.9  2445.1   599.8 2452.34   619.6 2460.07   649.4 2474.06   659.4 2477.74
   669.3 2479.18     719 2497.42   758.8 2507.59   798.6 2515.82   838.3 2528.93
#Mann= 3 , 0 , 0
       0     .06       0   423.3    .045       0   438.3     .06       0
Bank Sta=423.3,438.3
XS Rating Curve= 0 ,0
Exp/Cntr=0.3,0.1

Type RM Length L Ch R = 1 ,4860.1  ,455.9,439.2,421.1
XS GIS Cut Line= 3
     1893229.766      162035.787     1892866.506       161745.06
     1892591.782       161507.69
#Sta/Elev= 30
       0 2486.78    29.7 2485.91    89.1 2475.49   108.9 2478.79   158.4 2469.36
     198 2453.22   207.9 2452.49   217.8 2454.24   227.7 2451.89   247.5 2452.36
   267.3 2445.75   277.2 2445.72   287.1 2442.49   346.5 2410.48   405.4    2404
   415.8 2403.89   420.4 2403.96   435.6 2404.51   465.3 2411.58     534 2442.02
   553.6 2454.81     583  2469.1   602.6 2476.63   641.9 2497.33   661.5 2512.23
   671.3 2517.38   730.2 2547.82   759.6 2560.22   779.3 2574.83   828.3 2601.06
#Mann= 3 , 0 , 0
       0     .06       0   405.4    .045       0   420.4     .06       0
Bank Sta=405.4,420.4
XS Rating Curve= 0 ,0
Exp/Cntr=0.3,0.1

Type RM Length L Ch R = 1 ,4420.9  ,386.4,390.4,394.3
XS GIS Cut Line= 3
     1893440.946      161401.607     1893031.446      161401.607
     1892621.946      161401.607
#Sta/Elev= 30
       0 2601.47      20 2591.58    79.9 2570.38    99.9    2559   159.8 2534.39
   169.8 2526.47   239.7 2490.78   249.7 2478.84   259.7 2471.24   319.6  2437.3
   329.6  2427.2   349.6 2414.46   359.6 2410.14     402 2402.01     417 2400.48
   419.5 2400.47   449.4 2404.69   479.4 2417.03   499.4 2431.13   559.3 2459.57
   579.3 2474.31   639.2 2505.36   649.2 2514.62   659.2 2521.35   719.1 2553.31
   729.1 2562.36   739.1 2568.95     799 2598.98     809 2607.14     819 2612.82
#Mann= 3 , 0 , 0
       0     .06       0     402    .045       0     417     .06       0
Bank Sta=402,417
XS Rating Curve= 0 ,0
Exp/Cntr=0.3,0.1

Type RM Length L Ch R = 1 ,4030.1  ,375.6,384.2,392.8
XS GIS Cut Line= 3
     1893454.708       161148.25     1893103.784      161030.634
     1892651.773      160957.742
#Sta/Elev= 30
       0 2578.46    29.2 2572.99    58.4 2562.07   126.6 2531.69   194.8 2511.92
   204.5 2504.37   214.3 2499.19   272.7 2470.79   282.4 2464.81   292.2 2456.07
   370.1 2410.16   380.1 2405.65   406.8 2398.72   419.9 2396.73   421.8 2396.76
   439.8 2397.89   449.7 2400.05   469.6 2407.24   519.4 2426.59   529.4 2431.39
   539.3 2438.21     609 2467.28   618.9 2474.62   648.8 2485.76   688.6 2497.92
   698.6 2503.95   768.2 2527.59   778.2 2536.92   788.2 2543.75     828 2565.55
#Mann= 3 , 0 , 0
       0     .06       0   406.8    .045       0   421.8     .06       0
Bank Sta=406.8,421.8
XS Rating Curve= 0 ,0
Exp/Cntr=0.3,0.1

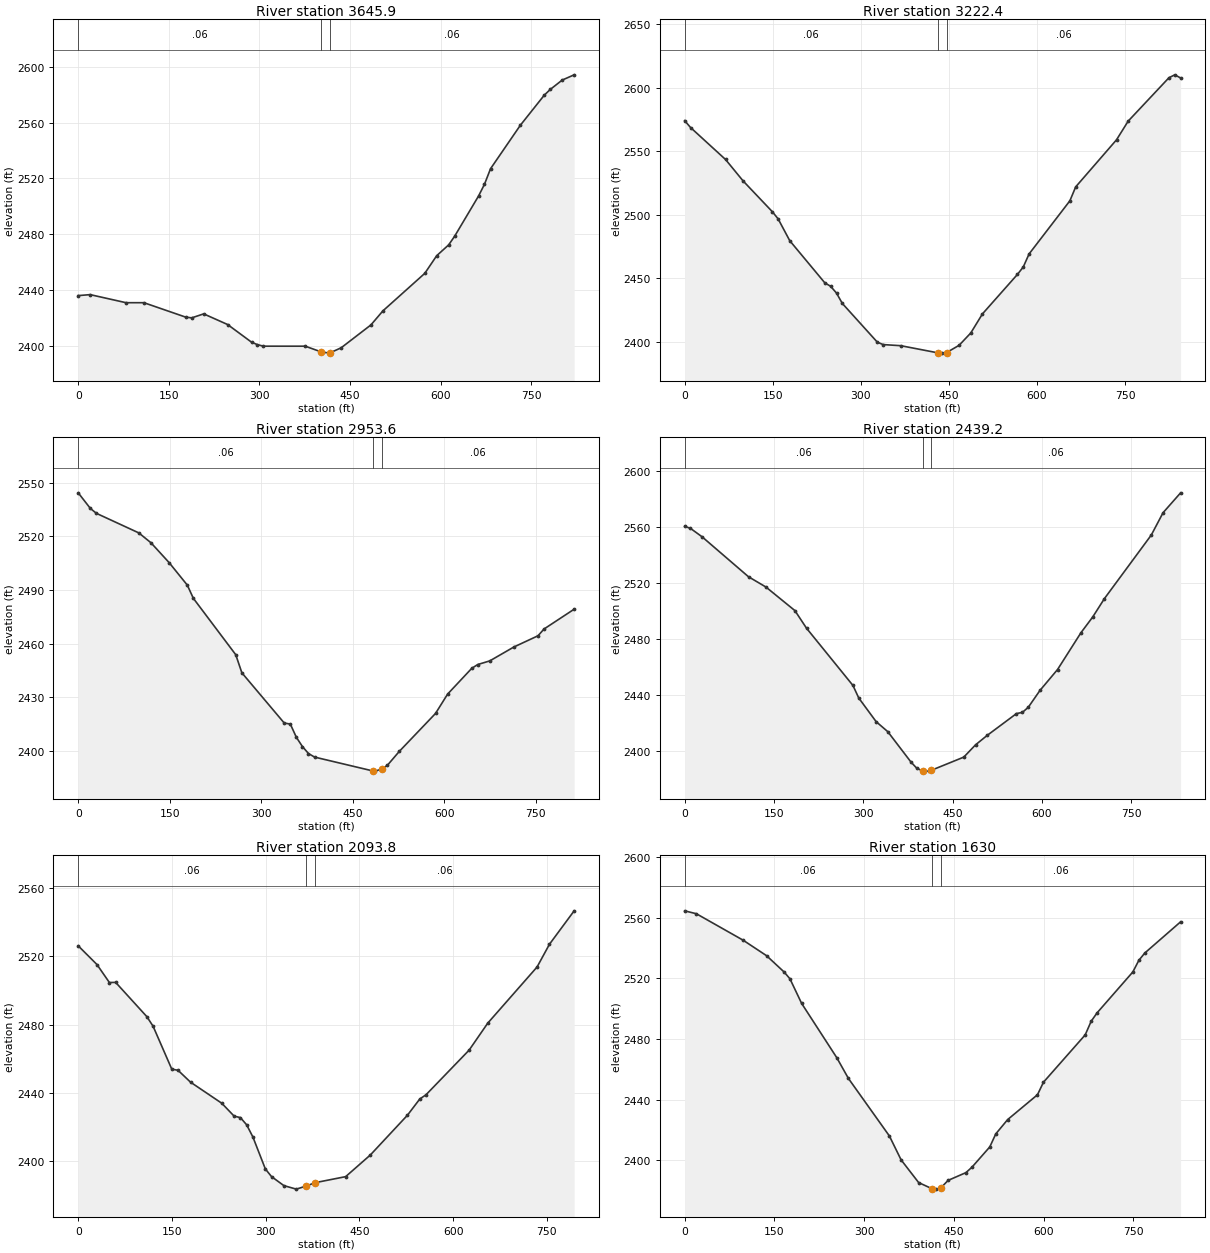
Type RM Length L Ch R = 1 ,3645.9  ,433.9,423.4,412.9
XS GIS Cut Line= 2
     1893604.497       160899.44      1892887.42      160499.066
#Sta/Elev= 30
       0 2436.28    19.8 2436.98    79.2 2431.21   108.8 2431.21   178.1 2420.88
     188 2420.38   207.8 2423.22   247.4 2415.61     287    2403   296.8 2401.21
   306.7 2400.13     376 2400.12   401.8 2396.12   415.6 2395.16   416.8 2395.33
   435.4 2398.96   484.8 2415.34   504.6 2425.37   573.9 2452.17   593.7 2464.82
   613.5 2472.55   623.4 2478.73     663 2507.49   672.8 2515.87   682.8 2526.97
   732.2 2558.06   771.8 2579.56   781.7 2583.65   801.5 2590.36   821.3 2594.11
#Mann= 3 , 0 , 0
       0     .06       0   401.8    .045       0   416.8     .06       0
Bank Sta=401.8,416.8
XS Rating Curve= 0 ,0
Exp/Cntr=0.3,0.1

Type RM Length L Ch R = 1 ,3222.4  ,266.4,268.7,271.2
XS GIS Cut Line= 3
     1893742.613      160335.404     1893235.798      160315.346
     1892905.168      160383.023
#Sta/Elev= 30
       0 2574.12      10 2568.72    69.6 2543.54    99.4 2526.72   149.2 2502.48
   159.1 2496.84     179 2479.59   238.7 2446.42   248.6 2443.71   258.6 2438.37
   268.5 2430.21   328.2 2399.68   338.1 2397.81     368 2396.95   431.3 2391.31
   437.6 2391.09   446.3 2391.58   467.4 2397.25   487.3 2406.96   507.2 2421.99
   566.8 2453.08   576.7 2458.92   586.6 2469.18   656.1 2511.03     666 2521.99
   735.5 2559.03   755.4 2573.75   824.8 2607.91   834.8  2610.2   844.7 2607.72
#Mann= 3 , 0 , 0
       0     .06       0   431.3    .045       0   446.3     .06       0
Bank Sta=431.3,446.3
XS Rating Curve= 0 ,0
Exp/Cntr=0.3,0.1

Type RM Length L Ch R = 1 ,2953.6  ,503.6,514.4,511
XS GIS Cut Line= 3
     1893834.501      160131.697     1893333.298      160058.222
     1893030.444      160012.492
#Sta/Elev= 30
       0 2544.38    19.9 2535.66    29.8  2532.9    99.3 2521.95   119.2 2516.44
     149 2505.31   178.8 2492.71   188.7 2485.32   258.2 2453.75   268.2 2443.63
   337.7 2415.48   347.6 2414.94   357.6 2407.47   367.5 2402.32   377.4 2398.43
   387.4 2396.44   482.6 2388.71   486.7 2388.58   497.6 2389.76   506.6  2391.8
   526.3 2399.66   585.6 2420.87   605.4  2431.7   644.9  2446.1   654.8 2448.26
   674.5 2450.29     714 2458.07   753.6 2464.36   763.4 2468.14   812.8 2479.23
#Mann= 3 , 0 , 0
       0     .06       0   482.6    .045       0   497.6     .06       0
Bank Sta=482.6,497.6
XS Rating Curve= 0 ,0
Exp/Cntr=0.3,0.1

Type RM Length L Ch R = 1 ,2439.2  ,342.3,344.8,347.3
XS GIS Cut Line= 3
     1893977.362      159892.672     1893651.683       159716.54
     1893270.174      159454.968
#Sta/Elev= 30
       0 2560.59     9.7 2559.12    29.2 2553.11   107.2  2524.6   136.4  2517.3
   185.1 2500.47   204.6 2487.92   282.6 2447.07   292.3 2438.16   321.5 2421.28
     341 2414.17   380.1 2392.42   389.9 2388.01   399.4 2386.16   409.6    2386
   414.4 2386.63   468.7    2396   488.4 2404.73     508 2411.49   557.2 2427.05
   567.1 2427.89   576.9 2431.48   596.6 2443.54   626.1 2458.44   665.5 2484.74
   685.2 2495.92   704.9 2509.06   783.6 2554.39   803.3 2570.27   832.8 2584.46
#Mann= 3 , 0 , 0
       0     .06       0   399.4    .045       0   414.4     .06       0
Bank Sta=399.4,414.4
XS Rating Curve= 0 ,0
Exp/Cntr=0.3,0.1

Type RM Length L Ch R = 1 ,2093.8  ,478.8,463.5,433.1
XS GIS Cut Line= 3
     1893936.262      159799.144     1893895.974      159502.416
     1893515.485       159187.25
#Sta/Elev= 30
       0 2526.06      30 2515.11    49.9  2504.6    59.9 2504.69   109.8 2484.66
   119.8 2479.05   149.7 2453.97   159.7 2453.31   179.7 2446.36   229.6 2434.07
   249.5 2426.49   259.5 2425.65   269.5 2421.44   279.5  2414.3   299.4 2395.65
   309.3 2391.16   329.1 2385.88   348.9 2383.84   364.2 2385.57   379.2 2387.62
   427.9 2391.14   467.4 2403.79   526.7 2427.01   546.5 2436.52   556.4 2438.97
   625.5 2465.11   655.2 2480.83   734.2  2513.7     754 2526.98   793.5 2546.51
#Mann= 3 , 0 , 0
       0     .06       0   364.2    .045       0   379.2     .06       0
Bank Sta=364.2,379.2
XS Rating Curve= 0 ,0
Exp/Cntr=0.3,0.1

Type RM Length L Ch R = 1 ,1630    ,384.4,393.1,377.8
XS GIS Cut Line= 3
     1894377.643      159128.085     1893959.212      159087.249
     1893551.373      159061.698
#Sta/Elev= 30
       0 2564.64    19.6 2562.71    97.8 2545.22   136.9    2535   166.2 2524.24
     176 2519.73   195.5  2503.5   254.2 2467.67   273.8 2453.88   342.2 2415.93
   361.8 2400.14   391.1 2385.15   412.9 2381.17   420.4  2380.8   427.9 2381.51
   440.4 2386.58   470.2  2391.7   480.2 2395.26   510.1  2408.7   520.1 2417.29
     540 2426.76   589.8 2443.14   599.8 2451.42   669.6  2482.7   679.6 2491.72
   689.5 2497.27   749.3  2524.3   759.3 2531.96   769.3  2536.8   829.1 2557.38
#Mann= 3 , 0 , 0
       0     .06       0   412.9    .045       0   427.9     .06       0
Bank Sta=412.9,427.9
XS Rating Curve= 0 ,0
Exp/Cntr=0.3,0.1

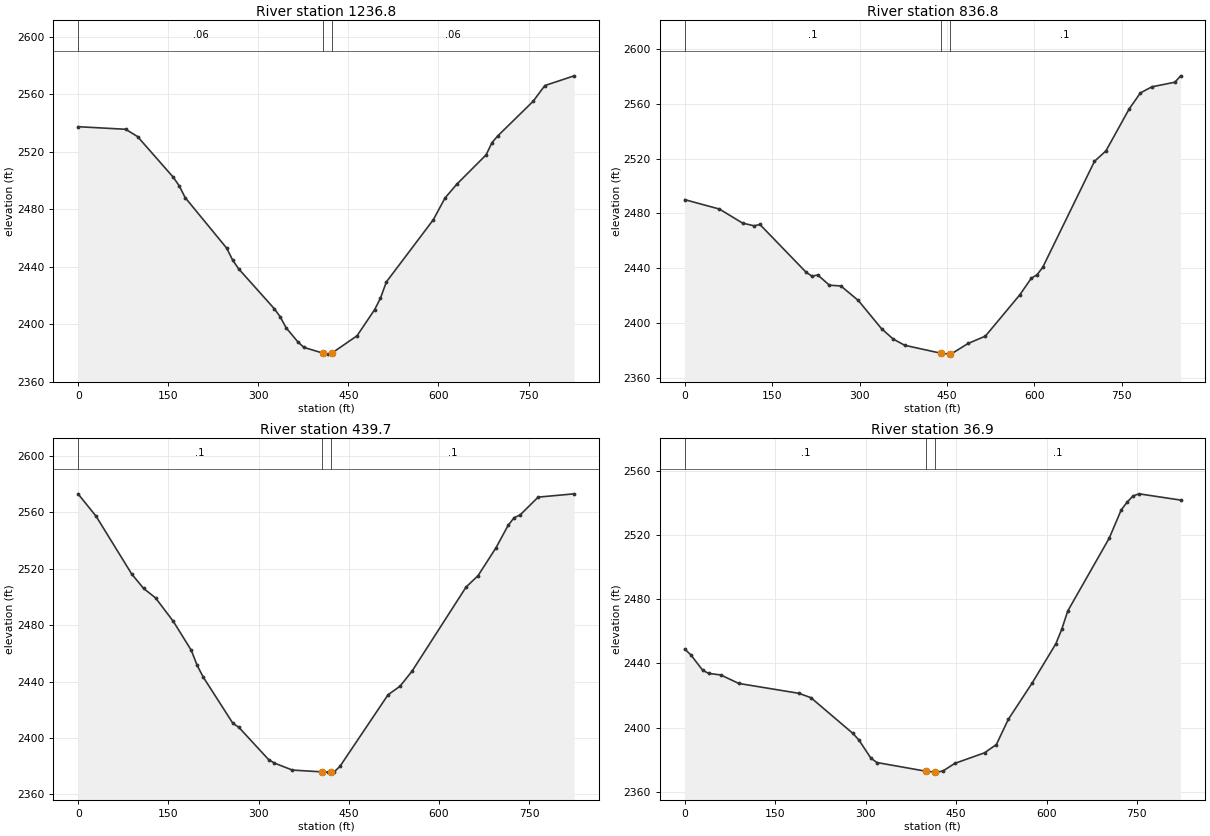
Type RM Length L Ch R = 1 ,1236.8  ,378.4,399.8,420.1
XS GIS Cut Line= 3
      1894427.15      158873.192     1894030.617       158749.17
     1893639.671      158623.757
#Sta/Elev= 30
       0 2537.43    79.1 2535.63    98.9 2530.55   158.3  2502.3   168.2 2496.32
   178.1 2488.15   247.3 2452.97   257.2 2444.69   267.1 2438.65   326.4 2410.95
   336.3 2405.33   346.2 2397.65     366 2387.72   375.9 2383.96     408 2379.92
   415.5 2379.28     423 2380.13   464.4 2392.05   493.7 2410.23   503.4 2418.16
   513.2 2429.46   591.4 2472.72     611 2487.89   630.5 2497.42   679.4 2517.86
   689.2 2526.42     699 2531.11   757.6 2555.07   777.2 2566.04     826  2572.8
#Mann= 3 , 0 , 0
       0     .06       0     408    .045       0     423     .06       0
Bank Sta=408,423
XS Rating Curve= 0 ,0
Exp/Cntr=0.3,0.1

Type RM Length L Ch R = 1 ,836.8   ,400.3,397,391.1
XS GIS Cut Line= 3
     1894485.647      158780.944     1894214.958      158425.345
     1894043.023      158059.743
#Sta/Elev= 30
       0 2490.04    59.6 2483.17    99.3 2472.93   119.2 2470.92   129.1 2471.91
   208.6 2436.93   218.5 2434.23   228.4 2435.04   248.3 2427.62   268.1 2427.02
   297.9 2416.46   337.7 2395.89   357.5 2388.41   377.4 2383.76   439.4 2377.97
   454.4 2377.32   456.8  2377.3   486.3 2385.08   515.9 2390.43     575 2420.58
   594.7  2432.7   604.6  2435.2   614.4 2440.72   703.1 2517.99   722.8 2525.63
   762.2 2555.92   781.9 2567.91   801.6 2572.38   841.1 2575.73   850.9 2580.39
#Mann= 3 , 0 , 0
       0      .1       0   439.4    .045       0   454.4      .1       0
Bank Sta=439.4,454.4
XS Rating Curve= 0 ,0
Exp/Cntr=0.3,0.1

Type RM Length L Ch R = 1 ,439.7   ,412.1,402.4,392
XS GIS Cut Line= 3
      1894790.63      158480.374     1894497.322      158186.115
      1894250.99      157859.249
#Sta/Elev= 30
       0 2572.97    29.7 2557.26      89 2516.24   108.8 2506.02   128.6 2499.33
   158.3 2482.59     188 2462.18   197.8 2451.48   207.7  2443.3   257.2 2410.39
   267.1 2407.55   316.6 2384.64   326.4 2382.14   356.1 2377.19   404.7 2375.93
   415.5 2375.73   419.7 2375.76   425.5 2375.81   435.4 2379.88   515.3 2430.61
   535.3  2436.7   555.2 2447.36   645.1 2507.03     665 2515.12     695 2535.01
     715 2550.78   724.9  2556.2   734.9 2558.14   764.9  2570.8   824.8 2573.14
#Mann= 3 , 0 , 0
       0      .1       0   404.7    .045       0   419.7      .1       0
Bank Sta=404.7,419.7
XS Rating Curve= 0 ,0
Exp/Cntr=0.3,0.1

Type RM Length L Ch R = 1 ,36.9    ,38.1,36.9,33.9
XS GIS Cut Line= 3
     1895133.802      158029.647      1894751.43      157885.732
     1894377.607      157708.257
#Sta/Elev= 30
       0 2448.94      10 2445.44    29.9  2435.7    39.9 2433.75    59.8  2432.8
    89.7  2427.5   189.3 2421.34   209.3 2418.62     279  2396.3     289 2392.16
   308.9 2380.83   318.9 2378.14   400.8 2372.67   415.8 2372.19   418.4 2372.16
   428.3 2372.88     448 2377.62   497.2 2384.21   516.9 2389.39   536.6 2405.05
     576 2427.65   615.5 2452.25   625.3 2461.31   635.2 2472.68   704.1 2518.21
   723.8 2535.71   733.7 2540.63   743.6 2544.52   753.4 2545.81   822.4 2541.91
#Mann= 3 , 0 , 0
       0      .1       0   400.8    .045       0   415.8      .1       0
Bank Sta=400.8,415.8
XS Rating Curve= 0 ,0
Exp/Cntr=0.3,0.1

Chan Stop Cuts=-1
Use User Specified Reach Order=0
Composite Channel Slope=5